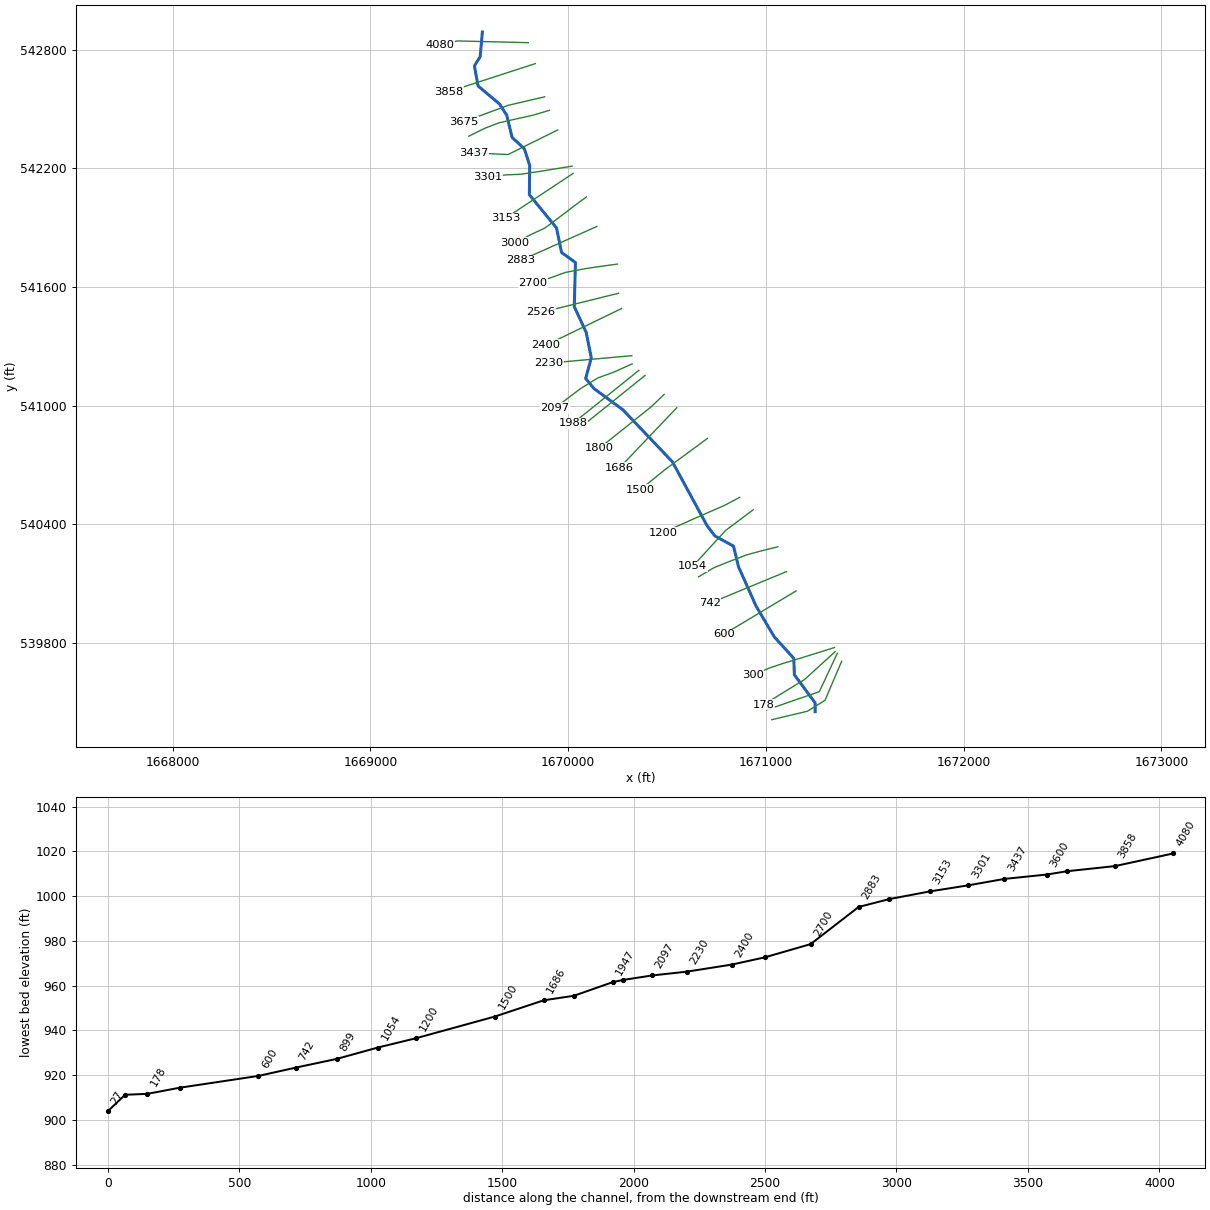
--- TurkeyRnT1.prj (project) ---

Proj Title=TurkeyRnT1
Current Plan=p01
Default Exp/Contr=0,0
English Units
Geom File=g01
Flow File=f01
Plan File=p01
BEGIN DESCRIPTION:
---------- MODELED AS PART OF WVEM CTP PROGRAM, 2025----------
Stream Name: Turkey Run Tributary 1
Flood Zone: AFH
Marshall County, WV
HEC-RAS Version: RAS 6.6
Vertical Datum: NAVD88
Projection: NAD 1983 StatePlane West Virginia N FIPS 4701 (US Feet)
Terrain: 1-meter West Virginia FEMA R3 South Central (collected 2018-2019)
Land Use: 2024 NLCD
Hydrologic Method:
Duda et al., "Estimation of magnitude and frequency of floods for rural, unregulated streams in and near Virginia and West Virginia." September 8, 2025.
Additional Model Notes:
None
END DESCRIPTION:
DSS Export Rating Curves= 0
DSS Export Rating Curve Sorted= 0
DSS Export Volume Flow Curves= 0
DXF OffsetX= 0
DXF OffsetY= 0
DXF ScaleX= 0
DXF ScaleY= 0

--- TurkeyRnT1.p01 (plan) ---

Plan Title=Floodplain
Program Version=6.60
Short Identifier=Floodplain
Geom File=g01
Flow File=f01
Subcritical Flow
K Sum by GR= 0
Std Step Tol= 0.01
Critical Tol= 0.01
Num of Std Step Trials= 20
Max Error Tol= 0.3
Flow Tol Ratio= 0.001
Split Flow NTrial= 30
Split Flow Tol= 0.02
Split Flow Ratio= 0.02
Log Output Level= 0
Friction Slope Method= 1
Unsteady Friction Slope Method= 2
Unsteady Bridges Friction Slope Method= 1
Parabolic Critical Depth
Global Vel Dist= 0 , 0 , 0
Global Log Level= 0
CheckData=False
Encroach Param=-1 ,0,0, 0
Flow Ratio Tolerance=0.1
Flow Ratio Min Ratio=0.5
Flow Ratio Max Ratio=4
Flow Ratio Max Iterations= 10
Mapping Interval=1HOUR
Computation Time Step Use Courant=        0
Computation Time Step Use Time Series=    0
Computation Time Step Count To Double=0
Computation Time Step Max Doubling=0
Computation Time Step Max Halving=0
Computation Time Step Residence Courant=0
Run HTab= 0
Run UNet= 0
Run Sediment= 0
Run PostProcess= 0
Run WQNet= 0
Run RASMapper=-1
UNET Theta= 0
UNET Theta Warmup= 0
UNET ZTol= 0
UNET ZSATol= 0
UNET MxIter= 0
UNET Max Iter WO Improvement= 0
UNET MaxInSteps= 0
UNET DtIC= 0
UNET DtMin= 0
UNET MaxCRTS= 0
UNET WFStab= 0
UNET SFStab= 0
UNET WFX= 1
UNET SFX= 1
UNET Gravity=32.17405
UNET 1D Methodology=Finite Difference
UNET DSS MLevel= 1
UNET Pardiso=0
UNET DZMax Abort= 0
UNET Use Existing IB Tables= 0
UNET Froude Reduction=False
UNET Froude Limit= 0
UNET Froude Power= 0
UNET D1 Cores= 0
UNET WindReference=Eulerian
UNET WindDragFormulation=Hsu (1988)
UNET D2 Coriolis=0
UNET D2 Cores= 0
UNET D2 Theta= 1
UNET D2 Theta Warmup= 1
UNET D2 Z Tol= 0.01
UNET D2 Volume Tol= 0.01
UNET D2 Max Iterations= 20
UNET D2 Advanced Convergence=0
UNET D2 WS Max Tol=0.15
UNET D2 WS RMS Tol=0.002
UNET D2 WS Stall Tol=1
UNET D2 Equation= 0
UNET D2 RampUpFraction=0.1
UNET D2 TimeSlices= 1
UNET D2 Turbulence Formulation=Non-Conservative (original)
UNET D2 Eddy Viscosity=0.3
UNET D2 Transverse Eddy Viscosity=0.1
UNET D2 Smagorinsky Mixing=0
UNET D2 BCVolumeCheck=0
UNET D2 Cores=0
UNET D2 SolverType=PARDISO (Direct)
UNET D2 Minimum Iterations= 3
UNET D2 Maximum Iterations= 30
UNET D2 Restart Number= 10
UNET D2 Relaxation Coeff=1.3
UNET D2 SOR Precondition Iterations= 10
UNET D2 ILUT Maximum Fill= 8
UNET D2 ILUT Tolerance=1E-08
UNET D2 Convergence Tolerance=0.00001
PS Theta= 1
PS WS Tol= 0.01
PS Volume Tol= 0.01
PS Max Iterations= 20
PS Equation= 0
PS Advance Time Step=-1
PS Target Courant=0.9
PS Time Slices= 1
PS Iterate With 2D=0
PS Project Initial WSE from DS=-1
PS Ramp Up Initial WSE from US=-1
PS Cores=0
UNET D1D2 MaxIter= 0
UNET D1D2 ZTol=0.01
UNET D1D2 QTol=0.1
UNET D1D2 MinQTol=1
Write IC File= 0
Write IC File at Fixed DateTime=0
Write IC File at Sim End=0
Echo Input=False
Echo Parameters=False
Echo Output=False
Write Detailed= 0
HDF Write Warmup=0
HDF Write Time Slices=0
HDF Flush=0
HDF Compression= 1
HDF Chunk Size= 1
HDF Spatial Parts= 1
HDF Use Max Rows=0
HDF Fixed Rows= 1
Calibration Method= 0
Calibration Iterations= 20
Calibration Max Change=0.05
Calibration Tolerance=0.2
Calibration Maximum=1.5
Calibration Minimum=0.5
Calibration Optimization Method= 1
WQ AD Non Conservative
WQ ULTIMATE=-1
WQ Max Comp Step=1HOUR
WQ Output Interval=15MIN
WQ Output Selected Increments= 0
WQ Create Restart=0
WQ Fixed Restart=0
WQ System Summary=0
WQ Write To DSS=0
Sorting and Armoring Iterations= 10
XS Update Threshold= 0.02
Bed Roughness Predictor= 0
Processes Affected by Predictor=Sediment Only
Hydraulics Update Threshold= 0.02
Energy Slope Method= 1
Volume Change Method= 1
Sediment Retention Method= 0
Sediment TS Multiplier= 1
Warm Up Method= 0
XS Weighting Method= 0
Number of US Weighted Cross Sections= 1
Number of DS Weighted Cross Sections= 1
Upstream XS Weight=0
Main XS Weight=1
Downstream XS Weight=0
Number of DS XS's Weighted with US Boundary= 1
Upstream Boundary Weight= 1
Weight of XSs Associated with US Boundary= 0
Number of US XS's Weighted with DS Boundary= 1
Downstream Boundary Weight= 0.5
Weight of XSs Associated with DS Boundary= 0.5
Percentile Method= 0
Sediment Output Level= 3
Mass or Volume Output= 0
Output Increment Type= 1
Profile and TS Output Increment= 1
Transport Output Increment 1
XS Output Flag= 0
XS Output Increment= 10
Read HDF5 Sediment Hotstart= 0
Sediment Hotstart Type= 0
Write Gradation File= 0
Read Gradation Hotstart= 0
Write HDF5 File= 1
Write Binary Output= 1
Write DSS Sediment File= 0
DSS Sediment Output Type= 1
SV Curve= 0
Specific Gage Flag= 0
Subcell Erosion Methods= 0
Subcell Deposition Methods= 0
Advection Scheme= 1
Matrix Solver= 0
Implicit Weighting Factor= 1
Maximum Outer Loop Convergence Iterations= 5
Convergence Maximum Absolute= 0.001
Convergence RMSE= 0.0001
Grain Fractions Max Abs Error= 0.001
Max Subgrid Regions= 1
Max Subgrid Length Scale= 3.402823E+38
Initial Layer Thickness= 3
Min Layer Thickness= 0.1
Max Layer Thickness= 6
Number of Layers= 5

--- TurkeyRnT1.f01 (steady flow) ---

Flow Title=Flow
Program Version=6.60
Number of Profiles= 1
Profile Names=P100yr
River Rch & RM=TurkeyRnT1,Main,4080
     766
Boundary for River Rch & Prof#=TurkeyRnT1,Main            , 1
Up Type= 0
Dn Type= 3
Dn Slope=0.069
DSS Import GetInterval= 0
DSS Import GetPeak= 0
DSS Import FillOption= 0

--- TurkeyRnT1.g01 (geometry) ---

Geom Title=Geometry
Program Version=6.60

River Reach=TurkeyRnT1      ,Main
Reach XY= 30
     1669566.678      542888.833     1669555.354      542764.244
     1669526.358      542717.323     1669544.747      542615.868
     1669653.393      542524.767     1669689.833      542467.407
     1669716.678      542356.189     1669778.909      542298.365
     1669805.775      542214.371     1669804.194        542065.7
     1669941.267      541898.576       1669967.1      541773.629
     1670037.218      541723.018     1670031.419      541499.483
      1670091.52      541369.791     1670117.353      541240.626
     1670088.884      541136.767      1670131.06      541085.629
     1670277.264      540978.417     1670527.622      540715.237
     1670702.671      540392.592     1670742.404      540340.334
     1670836.458      540289.0251670862.12956142 540183.80373685
     1670951.125        539984.8     1671043.334       539829.11
     1671141.422      539721.494     1671144.318      539638.233
     1671249.456      539496.045     1671249.369       539451.46

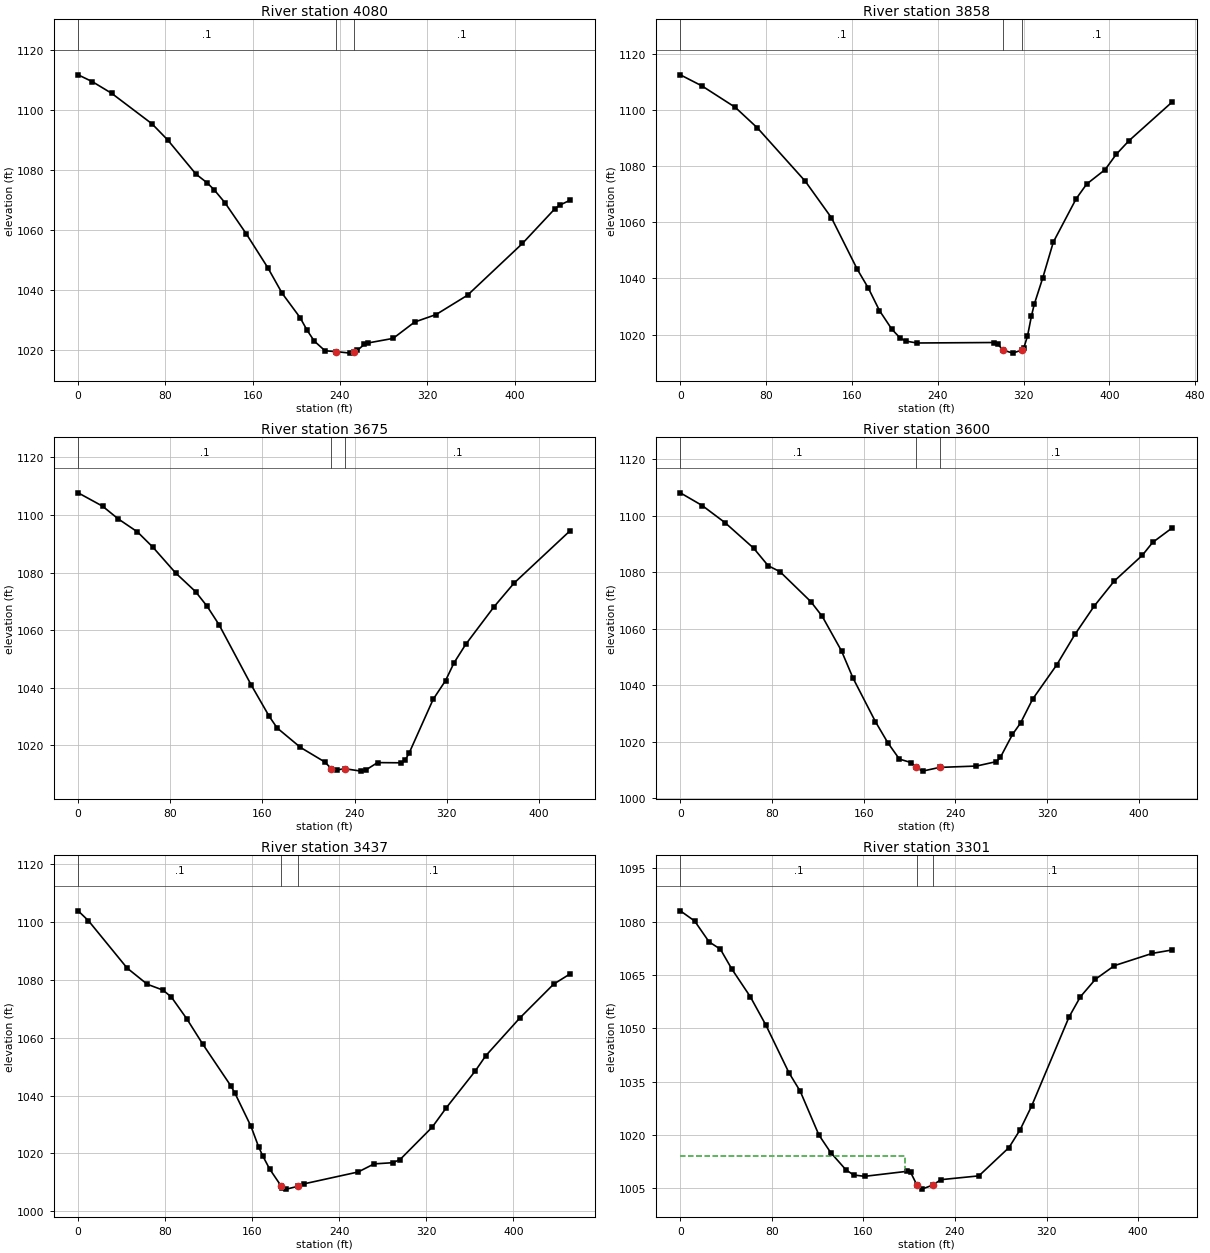
Type RM Length L Ch R = 1 ,4080    ,217.3,222.2,224.3
XS GIS Cut Line= 3
1669798.77255218542834.9604551921669440.85115605542843.570248226
1669349.83334397542825.120691724
#Sta/Elev= 30
       0 1111.59      13 1109.32    30.7 1105.45    67.7  1095.3      82 1089.97
     108 1078.58   118.1 1075.72   124.6  1073.4   134.5  1069.1   154.2 1058.68
   173.8 1047.49     187 1038.95   203.4 1030.89   209.9 1026.64   216.5 1023.05
   226.3 1019.84   236.2 1019.58   249.3 1019.06   252.6 1019.38   255.9 1019.98
   262.4    1022   265.7 1022.44   288.7 1023.96   308.4 1029.39   328.1 1031.89
   356.9 1038.32   407.2 1055.51   436.9 1067.03   441.3 1068.23   450.9 1069.91
#Mann= 3 ,-1,0
       0      .1       0   236.2    .045       0   252.6      .1       0
Bank Sta=236.2,252.6
XS Rating Curve= 0 ,0
Exp/Cntr(USF)=0,0
Exp/Cntr=0.3,0.1

Type RM Length L Ch R = 1 ,3858    ,180.7,183.6,184.6
XS GIS Cut Line= 2
1669834.45102582542729.0529494471669398.08211545542587.581750194
#Sta/Elev= 30
       0 1112.52    20.2 1108.56    51.2 1100.95    71.9  1093.6   116.5 1074.62
   140.9 1061.61     165 1043.24   175.4 1036.49   185.7 1028.54   197.2 1021.92
     205 1018.76   210.2 1017.68   220.7    1017   292.6 1017.17   296.1 1016.56
  300.751014.525   309.9 1013.39  318.741014.525   320.2 1015.17   323.7 1019.44
   327.4 1026.61     330 1030.77   337.9 1040.13   347.8 1052.94   369.1 1068.38
   378.9 1073.61   396.1 1078.76   406.4 1084.18   418.3 1089.04   458.7 1102.87
#Mann= 3 ,-1,0
       0      .1       0  300.75    .045       0  318.74      .1       0
Bank Sta=300.75,318.74
XS Rating Curve= 0 ,0
Exp/Cntr(USF)=0,0
Exp/Cntr=0.3,0.1

Type RM Length L Ch R = 1 ,3675    ,76.2,75,72.2
XS GIS Cut Line= 3
1669881.85256822542561.0645378721669697.54149877542518.224667676
1669474.37566333542435.533755437
#Sta/Elev= 30
       0 1107.69    21.2 1103.06    34.7 1098.67    51.5 1094.13      65 1088.78
    84.6  1079.9     102 1073.38   112.1 1068.25   122.3 1061.95   150.2 1041.05
     166 1030.06   172.8 1026.07   193.1 1019.31   214.1 1014.28  219.951011.923
   224.6 1011.47  231.451011.931   245.6 1011.08   249.8 1011.47     260 1014.04
   280.6 1013.97   284.1 1014.97   287.6 1017.49   308.3    1036   319.1 1042.53
   326.4 1048.66   336.5 1055.04   361.1  1068.1   378.6 1076.37   427.2 1094.52
#Mann= 3 ,-1,0
       0      .1       0  219.95    .045       0  231.45      .1       0
Bank Sta=219.95,231.45
XS Rating Curve= 0 ,0
Exp/Cntr(USF)=0,0
Exp/Cntr=0.3,0.1

Type RM Length L Ch R = 1 ,3600    ,160.1,162.2,165.3
XS GIS Cut Line= 6
1669905.23387626542492.6269264221669821.11101301542467.765755668
1669747.86279993542451.6509585081669650.35052776542429.473181337
1669579.66398934542402.1254670021669498.11920492542362.044182345
#Sta/Elev= 30
       0 1108.16    19.1 1103.66    39.1 1097.57      64 1088.56    76.7 1082.34
      87 1080.24   113.9 1069.64   123.9 1064.41   140.7 1052.18   150.8 1042.51
   170.3 1027.14   181.1 1019.68   191.2 1013.89   201.3 1012.66  205.751010.937
   211.4 1009.62  226.321010.938   258.5 1011.42   275.9 1012.99   279.4 1014.52
   289.9 1022.59     297 1026.67   307.5 1035.09   328.6 1047.27   344.4    1058
   361.1 1067.97   378.7 1076.89   403.3 1086.06   412.3 1090.61   429.4 1095.76
#Mann= 3 ,-1,0
       0      .1       0  205.75    .045       0  226.32      .1       0
Bank Sta=205.75,226.32
XS Rating Curve= 0 ,0
Exp/Cntr(USF)=0,0
Exp/Cntr=0.3,0.1

Type RM Length L Ch R = 1 ,3437    ,138.8,136.8,134.3
XS GIS Cut Line= 3
1669947.46110898542393.4730031781669696.48920896542269.197528566
1669524.60170186 542277.26736458
#Sta/Elev= 30
       0  1103.8     9.5 1100.37      45 1084.03    63.5 1078.44      78 1076.41
    85.7    1074    99.9 1066.47   114.6 1057.71   140.2 1043.41   143.9 1040.96
   158.9 1029.31   165.8 1022.33   169.5 1019.26     176 1014.61  186.791008.606
   187.8 1007.99   191.4 1007.66  201.691008.608   207.8  1009.5   257.3 1013.58
     272 1016.38   289.2 1016.79   295.8 1017.86   325.4 1029.07   338.5 1035.84
   364.8 1048.39   374.6 1053.73   405.8 1066.73     437 1078.47   452.1 1082.01
#Mann= 3 ,-1,0
       0      .1       0  186.79    .045       0  201.69      .1       0
Bank Sta=186.79,201.69
XS Rating Curve= 0 ,0
Exp/Cntr(USF)=0,0
Exp/Cntr=0.3,0.1

Type RM Length L Ch R = 1 ,3301    ,141.1,147.4,148.2
XS GIS Cut Line= 6
1670020.45214976542210.5015064181669934.08880542542196.442479417
1669860.06336293542184.3919785921669761.16789143542169.521273419
 1669685.7001946542166.3283664291669594.48515393 542155.73521176
#Sta/Elev= 30
       0 1083.08    12.5 1080.22    25.1 1074.36      35 1072.29      45 1066.71
    61.1 1058.95    74.9 1050.86    94.9 1037.55   104.8 1032.32   121.1 1020.03
   131.4 1015.09   144.7 1010.24   151.4 1008.78   161.1  1008.4   197.8  1009.8
   201.2 1009.56  206.791005.929   211.1  1004.8  220.561005.932   227.7 1007.46
   260.9 1008.53   287.2 1016.49     297 1021.53   306.9  1028.1   339.7 1053.22
   349.6  1058.9   362.8 1063.85   379.4 1067.67   412.4 1071.11   429.9 1072.08
#Mann= 3 ,-1,0
       0      .1       0  206.79    .045       0  220.56      .1       0
#XS Ineff= 2 , 0
          196.03 1014.25
Permanent Ineff=
       F       F
Bank Sta=206.79,220.56
XS Rating Curve= 0 ,0
Exp/Cntr(USF)=0,0
Exp/Cntr=0.3,0.1

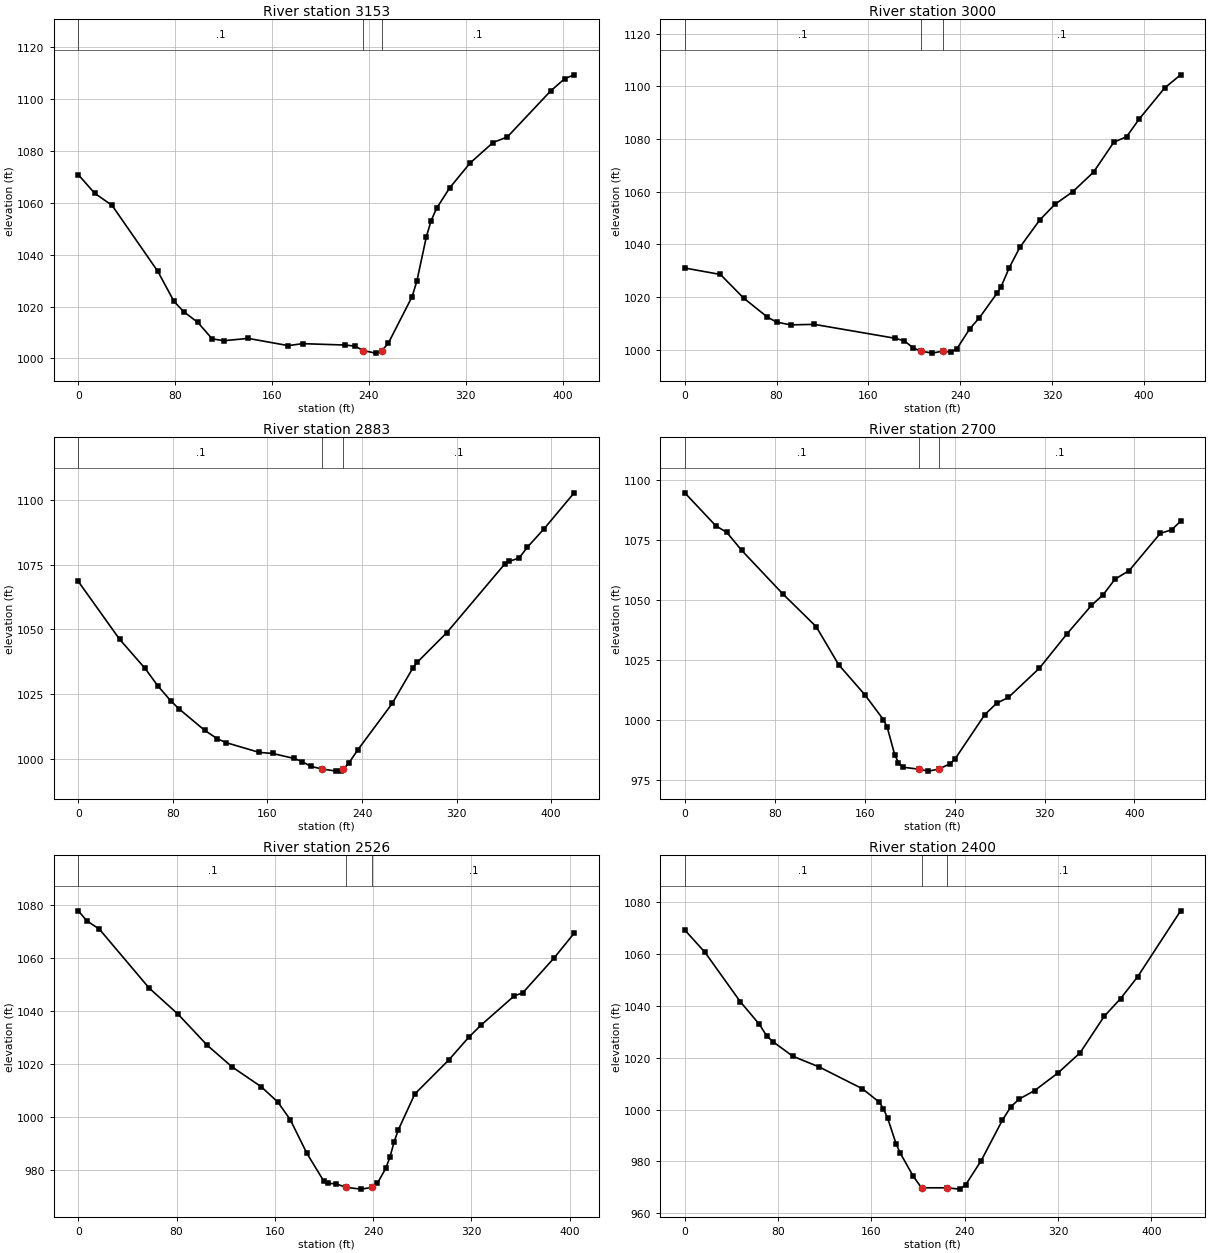
Type RM Length L Ch R = 1 ,3153    ,151.4,152.9,151.9
XS GIS Cut Line= 2
1670025.53677242542173.728678577 1669683.9137145541947.773270193
#Sta/Elev= 30
       0 1070.78    13.5 1063.65    27.9 1058.95    65.6  1033.6      79 1022.02
    86.9 1018.07    98.7  1013.9   110.5 1007.58     120 1006.84   140.4 1007.73
   173.4 1004.95   185.2 1005.71   220.6 1005.17   228.5 1004.76  235.431003.046
   245.5 1002.06  250.721003.046     256  1005.8   275.7 1023.79   279.6 1029.67
   287.5 1046.86   291.4 1053.05     296 1057.88   306.9  1065.8   323.6 1075.26
   342.6 1083.19   354.4 1085.33   390.2 1103.05   401.8 1107.78   409.6 1109.26
#Mann= 3 ,-1,0
       0      .1       0  235.43    .045       0  250.72      .1       0
Bank Sta=235.43,250.72
XS Rating Curve= 0 ,0
Exp/Cntr(USF)=0,0
Exp/Cntr=0.3,0.1

Type RM Length L Ch R = 1 ,3000    ,117.3,117.3,112.4
XS GIS Cut Line= 6
1670092.79354051542054.8741930131670022.34847142542002.867407262
  1669962.791832541957.2644800841669882.75098158541897.315453008
1669812.85971718541864.9549534171669730.72208618541822.621048585
#Sta/Elev= 30
       0 1030.97      31 1028.53    51.3 1019.55    71.7 1012.43    79.9 1010.44
    92.2 1009.39   112.8 1009.58   182.9 1004.33   191.1 1003.37   199.1 1000.61
  205.43999.4505   215.7  998.66   224.9  999.45   232.1     999   237.2 1000.41
   248.3 1007.92   256.7 1012.08   271.9 1021.34   275.5 1023.79   282.7 1031.11
     292 1038.89   309.3 1049.23   322.5 1055.17   338.1 1059.97   356.1 1067.37
   373.8 1078.73   384.9 1080.82   395.9 1087.53   418.1 1099.34     432 1104.32
#Mann= 3 ,-1,0
       0      .1       0  205.43    .045       0   224.9      .1       0
Bank Sta=205.43,224.9
XS Rating Curve= 0 ,0
Exp/Cntr(USF)=0,0
Exp/Cntr=0.3,0.1

Type RM Length L Ch R = 1 ,2883    ,181.9,182.8,178
XS GIS Cut Line= 2
1670145.68766418541905.6307932321669762.81877775541734.370940052
#Sta/Elev= 30
       0 1068.59    34.9  1046.2    56.5 1034.88    67.3 1028.11      78 1022.45
    85.2 1019.22   106.8 1010.95   117.6 1007.65   124.8 1006.18     153 1002.38
   164.3 1001.97   182.3 1000.05   189.5   998.8   196.6  996.95  206.48995.9236
   218.2  995.12   221.8  995.19  224.25995.9231     229  998.37   236.2 1003.24
   265.5 1021.33   282.9 1035.02   286.5 1037.21   311.7 1048.78   360.7 1075.36
   364.1 1076.35   372.8 1077.64   379.9  1081.9   393.9 1088.95   419.4 1102.92
#Mann= 3 ,-1,0
       0      .1       0  206.48    .045       0  224.25      .1       0
Bank Sta=206.48,224.25
XS Rating Curve= 0 ,0
Exp/Cntr(USF)=0,0
Exp/Cntr=0.3,0.1

Type RM Length L Ch R = 1 ,2700    ,171.3,174.1,173.4
XS GIS Cut Line= 6
  1670249.346377541715.0720510931670161.46367876 541703.28040801
1670085.73285909541691.8145516661669986.30392408541673.003893763
1669910.88839251541645.5577544271669820.86035734541617.181826919
#Sta/Elev= 30
       0 1094.83    27.5 1081.09    37.4 1078.26    50.7 1070.74    87.1 1052.63
   116.9 1038.89   136.9 1022.97     160 1010.53   176.7 1000.04   180.1  996.82
   186.8  985.27   190.1  982.05   193.8  980.16  208.39979.3173   216.8  978.51
  225.71979.3187   235.9  981.57   240.2  983.44   266.9 1002.12   277.4 1006.88
   287.9 1009.32   315.4  1021.5   340.2    1036   361.8 1047.79   372.3 1052.29
   382.7 1058.75   395.4 1062.35   422.9 1077.84   433.2 1079.41   441.1 1082.97
#Mann= 3 ,-1,0
       0      .1       0  208.39    .045       0  225.71      .1       0
Bank Sta=208.39,225.71
XS Rating Curve= 0 ,0
Exp/Cntr(USF)=0,0
Exp/Cntr=0.3,0.1

Type RM Length L Ch R = 1 ,2526    ,123.4,126.2,127.7
XS GIS Cut Line= 2
1670255.07877459541567.594329102 1669863.2434037541470.756296937
#Sta/Elev= 30
       0 1077.94     6.9 1074.16    17.1 1071.01    57.6 1048.73    81.3 1038.75
     105 1027.02   125.2 1018.85   148.9 1011.34   162.4 1005.55   172.5  998.89
   186.1   986.1   199.6   975.8     203  974.81   209.7   974.6  218.23973.2507
     230   972.6  239.45973.2505   243.5  974.88   250.3  980.54   253.7  984.78
     257  990.42   260.4  994.97   273.9 1008.62   301.6 1021.51   317.9 1030.14
     328 1034.76   354.7 1045.69   361.8 1046.93   387.3 1060.11   403.6 1069.48
#Mann= 3 ,-1,0
       0      .1       0  218.23    .045       0  239.45      .1       0
Bank Sta=218.23,239.45
XS Rating Curve= 0 ,0
Exp/Cntr(USF)=0,0
Exp/Cntr=0.3,0.1

Type RM Length L Ch R = 1 ,2400    ,172.7,169.9,165.3
XS GIS Cut Line= 6
1670270.27645326541490.3602301781670191.54235876541452.187078178
1670124.05594517541419.4669992631670034.07416975541375.840446085
1669966.58808425541343.1200390911669886.78673467541307.107972011
#Sta/Elev= 30
       0 1069.22    17.4 1060.56    47.5 1041.64    63.9 1032.89    70.1 1028.48
    75.4 1026.23    92.6 1020.57   115.2 1016.44   152.3 1008.03   166.6 1002.92
   170.2 1000.42   173.9  996.74   181.2  986.74   184.8  983.16   195.8  974.36
  202.98969.8601   224.9  969.86   235.7  969.35   240.7  970.94   254.1  980.32
   272.3  995.94   279.6 1001.14   286.9 1004.12   299.9 1007.34   319.7 1014.03
   338.9 1021.88   359.5 1035.91   373.6 1042.77   388.3 1051.24   425.1 1076.61
#Mann= 3 ,-1,0
       0      .1       0  202.98    .045       0   224.9      .1       0
Bank Sta=202.98,224.9
XS Rating Curve= 0 ,0
Exp/Cntr(USF)=0,0
Exp/Cntr=0.3,0.1

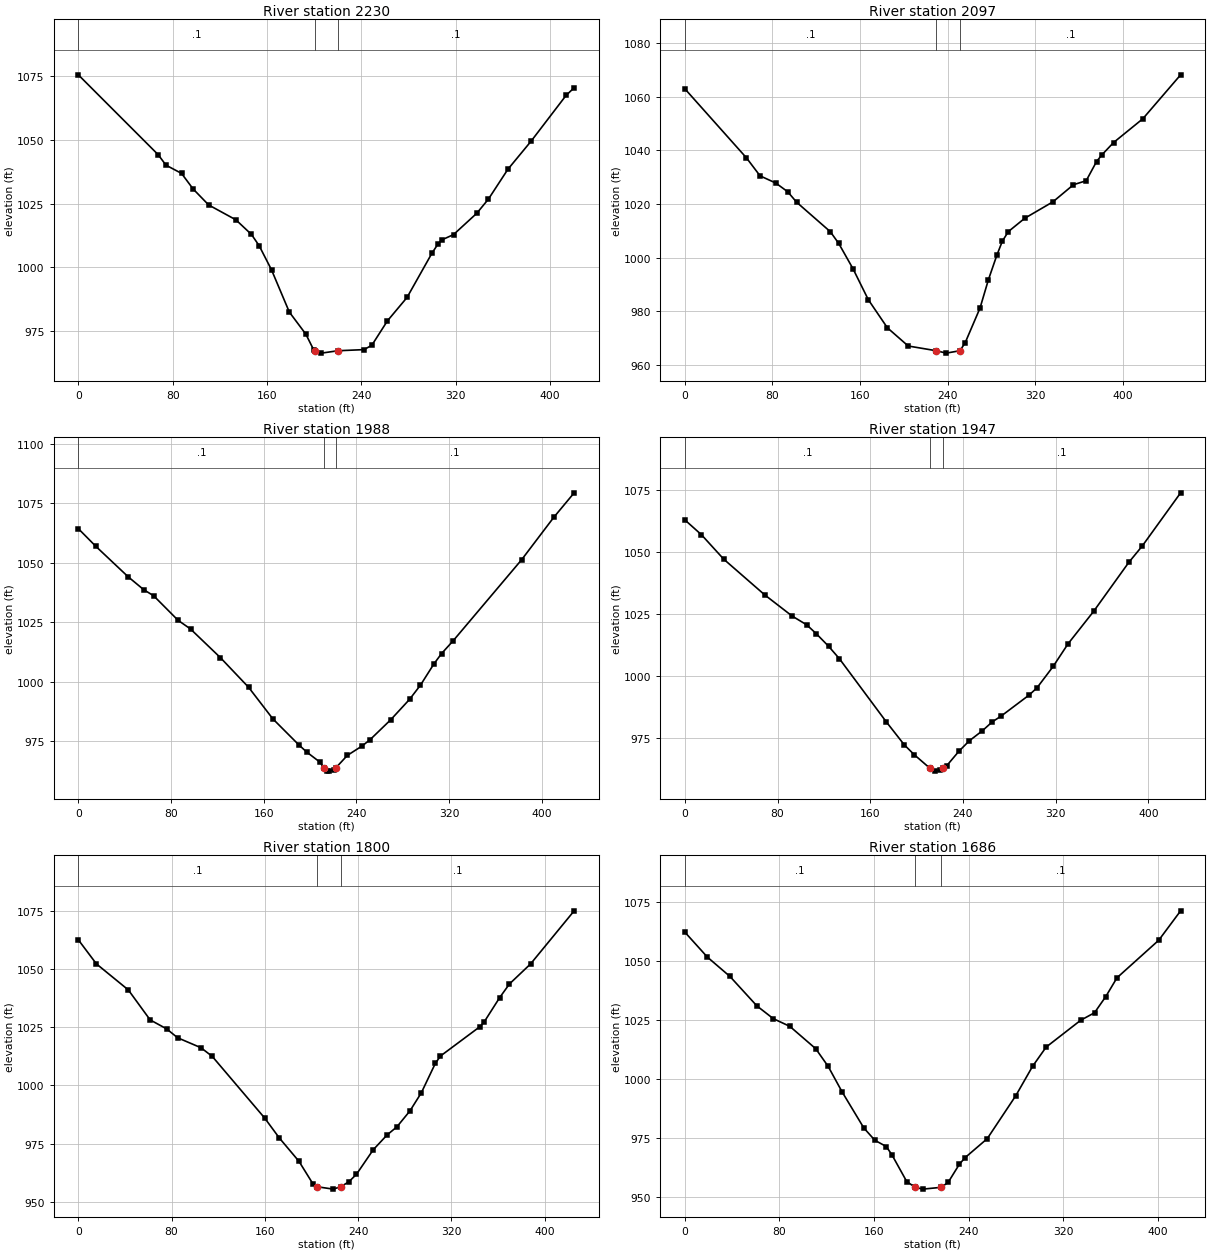
Type RM Length L Ch R = 1 ,2230    ,127,133,137.2
XS GIS Cut Line= 2
1670322.32740803541251.9740761211669903.59258377 541214.31484139
#Sta/Elev= 30
       0  1075.6    67.7 1044.21    74.3  1040.1    87.5 1036.86    97.3 1030.75
   110.5 1024.46   133.6 1018.61   146.8 1012.86   153.3 1008.45   163.8  998.95
   178.9  982.35   192.9  973.68   199.5  967.55   200.6967.1514   206.1  966.22
  220.08967.1529   242.3   967.6   248.9  969.35   262.1  978.92   278.7   988.1
   299.8 1005.48   304.9 1009.08   308.2 1010.73   318.1  1012.8   337.8 1021.17
   347.7 1026.75   364.2 1038.47   383.9 1049.53   413.6 1067.54   420.4 1070.52
#Mann= 3 ,-1,0
       0      .1       0   200.6    .045       0  220.08      .1       0
Bank Sta=200.6,220.08
XS Rating Curve= 0 ,0
Exp/Cntr(USF)=0,0
Exp/Cntr=0.3,0.1

Type RM Length L Ch R = 1 ,2097    ,106.7,109.1,111.9
XS GIS Cut Line= 6
1670324.15331401541210.5028502491670231.33033693 541168.89269726
1670149.77899083541138.9921665041670063.82181367541085.914516762
1670003.68217017541040.7302239241669933.87883209540987.645028248
#Sta/Elev= 30
       0  1062.9    56.3 1037.16    68.7 1030.48    83.1 1027.79    93.9 1024.57
   102.1 1020.65   132.8  1009.7   140.5 1005.31   153.5  995.91   167.5  984.37
   184.9  973.92   203.9  967.15   229.5  965.39   238.6   964.5  251.06  965.39
   255.8   968.3   269.4  981.25   277.1  991.84   284.8 1000.96   289.8 1006.18
   295.3 1009.74   310.2 1014.68     336 1020.82   354.7 1027.18   366.3 1028.66
   375.8 1035.82   380.5 1038.23   391.3 1042.88     418 1051.72   452.5 1068.08
#Mann= 3 ,-1,0
       0      .1       0   229.5    .045       0  251.06      .1       0
Bank Sta=229.5,251.06
XS Rating Curve= 0 ,0
Exp/Cntr(USF)=0,0
Exp/Cntr=0.3,0.1

Type RM Length L Ch R = 1 ,1988    ,40.9,40.7,40.5
XS GIS Cut Line= 2
1670357.99589129541177.8498683121670024.67390383540909.716313826
#Sta/Elev= 30
       0 1064.35    15.1 1056.93    43.1 1044.09    56.5 1038.69      65 1036.16
      86 1025.89    96.8 1022.21   122.5 1010.22   146.9  997.73   167.8  984.49
   190.1  973.62   197.1  970.51   208.1  966.43   212.3  963.84   214.9  962.74
   216.5  962.52   220.2  962.99  222.06963.8411   232.1  969.12   244.7  973.05
   251.6  975.67   269.5  984.08   285.8  992.67   295.2  998.64   306.8 1007.55
   313.4  1011.9   323.2 1017.15   382.4 1051.26   410.2  1069.1   427.8  1079.4
#Mann= 3 ,-1,0
       0      .1       0   212.3    .045       0  222.06      .1       0
Bank Sta=212.3,222.06
XS Rating Curve= 0 ,0
Exp/Cntr(USF)=0,0
Exp/Cntr=0.3,0.1

Type RM Length L Ch R = 1 ,1947    ,147.2,147.4,146.5
XS GIS Cut Line= 2
1670389.36013735541152.0204892111670056.03814989540883.886934724
#Sta/Elev= 30
       0 1063.02    14.4 1056.99    33.6 1047.13      69 1032.69    92.6 1024.16
   105.2  1020.6   113.6 1016.95   124.1 1011.93   133.4 1006.91   173.7   981.5
   189.4  972.11   197.8  968.21  211.59962.6237   215.6   961.5   219.8  961.86
  222.74 962.622   226.1  963.75   236.5  969.53   245.4  973.72   256.8  977.83
   265.2  981.37   273.2  983.83   296.8  992.14   303.8  995.11   317.8 1003.79
   330.7 1012.96   352.8 1026.09   383.1 1045.85   394.8 1052.52   427.8 1073.94
#Mann= 3 ,-1,0
       0      .1       0  211.59    .045       0  222.74      .1       0
Bank Sta=211.59,222.74
XS Rating Curve= 0 ,0
Exp/Cntr(USF)=0,0
Exp/Cntr=0.3,0.1

Type RM Length L Ch R = 1 ,1800    ,113.2,114.4,115.7
XS GIS Cut Line= 6
1670485.88232125541056.3758619281670422.64622726540995.352690011
1670364.08072759540948.5007495881670285.99361342540886.031714424
1670227.42811376540839.1797740011670159.10213493540784.519122168
#Sta/Elev= 30
       0 1062.64    15.5 1052.29    42.9 1041.08    61.6  1028.2    75.8 1024.32
    85.2 1020.51   105.2 1016.23   114.9  1012.5   159.9  985.97   172.5  977.38
   189.3  967.38   201.2  957.75  204.85 956.445   218.7  955.42  225.08956.4448
     232  958.54   238.6  961.78     253  972.34   264.9  978.72   273.3   982.2
   284.5  989.05   294.3  996.87   306.3  1009.5   310.7 1012.66   344.7 1025.34
   348.3  1027.4   361.5 1037.79   369.9 1043.66     388 1052.26   425.4  1075.1
#Mann= 3 ,-1,0
       0      .1       0  204.85    .045       0  225.08      .1       0
Bank Sta=204.85,225.08
XS Rating Curve= 0 ,0
Exp/Cntr(USF)=0,0
Exp/Cntr=0.3,0.1

Type RM Length L Ch R = 1 ,1686    ,186.3,185.6,182.4
XS GIS Cut Line= 2
1670549.59999299540988.7485784321670260.45866526540685.292258268
#Sta/Elev= 30
       0 1062.25    19.1 1051.65    38.2 1043.45      61 1030.97    74.8  1025.6
    88.8 1022.33   110.7 1012.86   121.2 1005.39   132.9  994.66   151.4  979.28
   160.7  974.09   170.4  971.43   175.2  967.86   187.7  956.56  194.92954.1761
   201.3  953.41  216.85954.1763   222.7  956.31   232.2  963.99     237  966.75
   255.7  974.78   279.8  992.94     294 1005.39   305.5 1013.55   334.7 1024.91
   346.4  1028.1   355.9 1034.93   365.4  1042.9   400.7  1058.8   419.2 1071.25
#Mann= 3 ,-1,0
       0      .1       0  194.92    .045       0  216.85      .1       0
Bank Sta=194.92,216.85
XS Rating Curve= 0 ,0
Exp/Cntr(USF)=0,0
Exp/Cntr=0.3,0.1

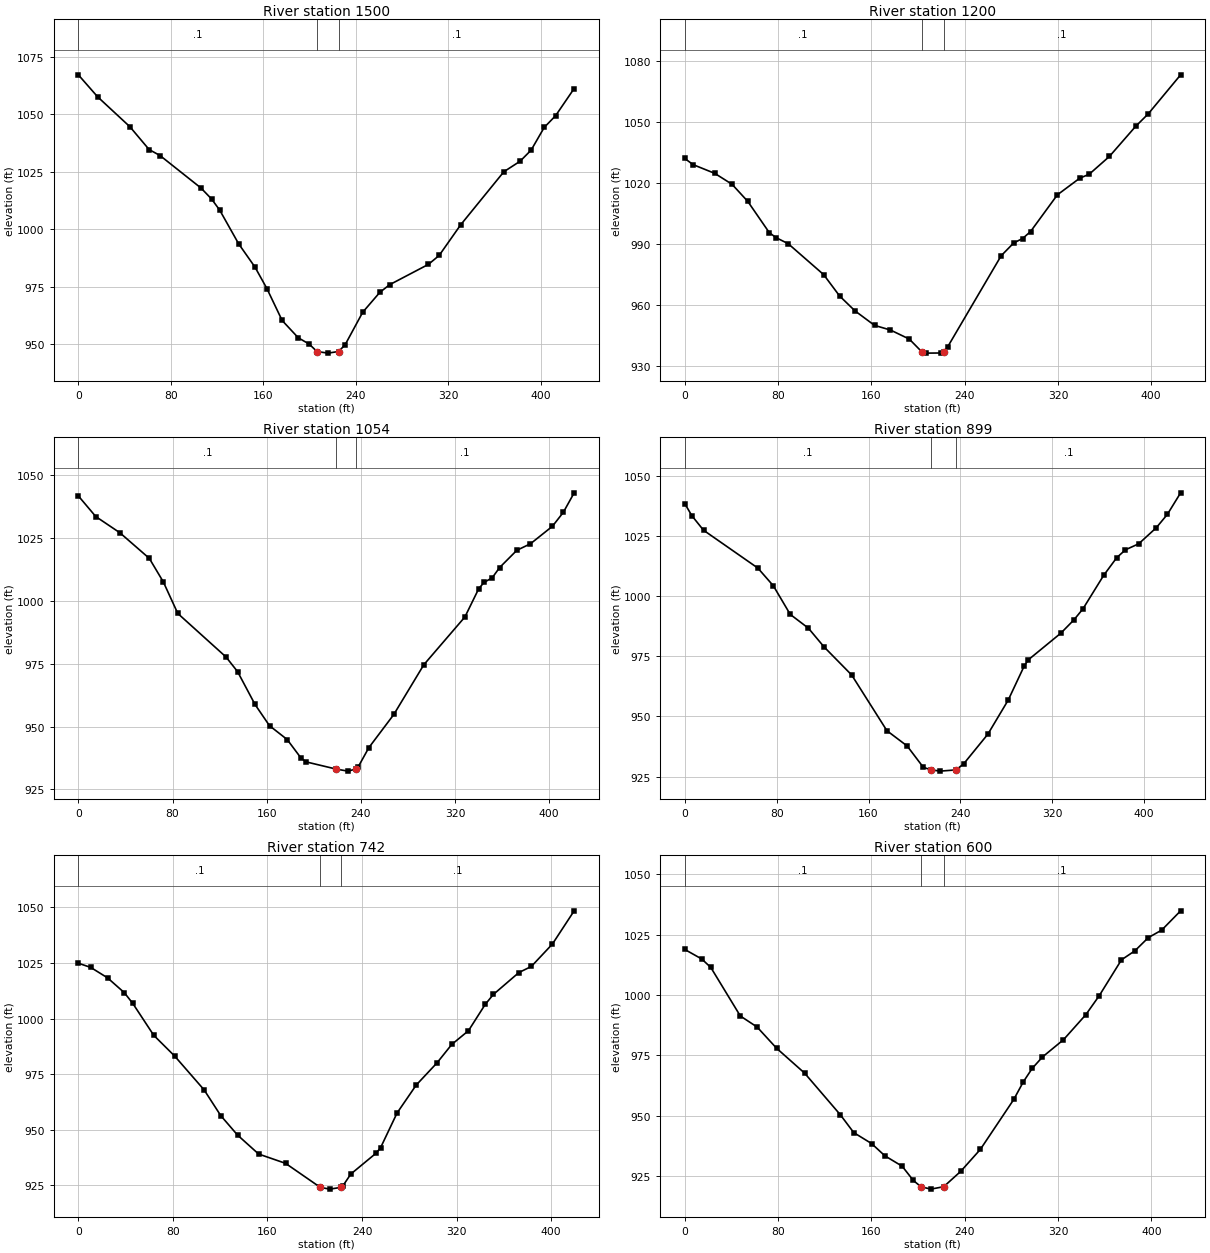
Type RM Length L Ch R = 1 ,1500    ,301.5,300,297.2
XS GIS Cut Line= 6
1670704.53313068540833.3543263381670634.03819293540781.520768583
1670573.61410117540737.0917235911670493.04897359540677.852668837
1670433.57763584540629.9600480941670363.86222409540573.006421834
#Sta/Elev= 30
       0 1067.22    16.7 1057.65    44.6 1044.64    61.2 1034.73    70.7  1032.1
   106.1 1017.98   115.2 1013.24   122.3 1008.36   138.7  993.69   152.8  983.59
   163.1  974.26   176.3  960.36   190.3  952.81   199.7   950.1   206.4  946.86
     216  946.16  225.06946.8615   230.7  949.72     246  963.95   260.8  972.59
   269.2   975.9   302.8  984.76   312.1  988.63   330.8 1002.02   368.1 1025.07
   382.1 1029.62   391.7 1034.48     403 1044.34   412.8 1049.41   428.9 1061.27
#Mann= 3 ,-1,0
       0      .1       0   206.4    .045       0  225.06      .1       0
Bank Sta=206.4,225.06
XS Rating Curve= 0 ,0
Exp/Cntr(USF)=0,0
Exp/Cntr=0.3,0.1

Type RM Length L Ch R = 1 ,1200    ,141.7,145.6,148.8
XS GIS Cut Line= 6
1670868.13680609540535.592454672 1670790.6133391540494.716880262
1670721.90153426 540464.655916751670630.29246551540424.559212178
1670561.80671009540393.9805331681670482.29505809540357.417942256
#Sta/Elev= 30
       0 1032.24     7.1 1029.22    25.7 1024.92    40.5 1019.55      54 1011.13
    72.4   995.8    78.2  993.31    88.7   990.3   119.1  975.08   132.8  964.55
     146  957.23   162.7  950.12   176.4  947.82   192.5  943.38  203.04937.2311
   206.9  936.46     220  936.53  222.17937.2299   225.5  939.62   271.3  984.38
   282.1   990.7   289.7  992.86   296.5  996.29   319.5 1014.35   338.7 1022.55
   346.8 1024.49   364.1 1033.24   386.6 1048.03   397.4 1054.19   425.2 1073.41
#Mann= 3 ,-1,0
       0      .1       0  203.04    .045       0  222.17      .1       0
Bank Sta=203.04,222.17
XS Rating Curve= 0 ,0
Exp/Cntr(USF)=0,0
Exp/Cntr=0.3,0.1

Type RM Length L Ch R = 1 ,1054    ,156.5,155,146.7
XS GIS Cut Line= 3
1670936.05636985540472.5776574861670795.47982649540367.266297507
1670629.72539477540186.098478999
#Sta/Elev= 30
       0 1041.66    14.8 1033.46    35.3 1027.01    60.3 1016.83    72.2 1007.48
    84.5  994.94   125.5  977.63   135.3  971.81   150.1  958.77   162.4  950.34
   177.4  944.85     189  937.59   193.4  935.97  219.06933.1002     229  932.29
  235.57933.1002   237.9  934.11   246.8  941.63     268   954.8   293.5  974.57
   328.4  993.56   340.1 1004.75   344.6 1007.27   351.6 1009.13   357.9  1013.2
   372.5 1020.04   384.1 1022.64   402.7 1029.57     412 1035.13   421.2 1042.88
#Mann= 3 ,-1,0
       0      .1       0  219.06    .045       0  235.57      .1       0
Bank Sta=219.06,235.57
XS Rating Curve= 0 ,0
Exp/Cntr(USF)=0,0
Exp/Cntr=0.3,0.1

Type RM Length L Ch R = 1 ,899     ,157.6,157.9,158.2
XS GIS Cut Line= 6
  1671061.368375540285.4771412611670976.07884742540264.486697674
1670903.32046276540244.7085220071670809.86920609540208.862465084
1670738.59441426540180.298873916  1670659.833745 540133.48860009
#Sta/Elev= 30
       0  1038.5     6.1 1033.49    16.3 1027.43    63.6 1011.69    77.1 1004.32
    91.8  992.43   107.6   986.7   121.2  978.93   145.3  967.22     176  944.05
   193.6  937.71   207.7  928.82   214.7  927.75   222.4  927.25  236.14  927.76
   242.8  930.27   263.9  942.64   281.6  956.81   295.7  971.15   299.2  973.58
   327.5  984.66   338.7   990.1   346.6  994.69   364.7 1008.66   376.1 1016.03
   383.7  1019.3   395.2 1021.78   410.5 1028.46   420.2 1034.05   431.7 1042.98
#Mann= 3 ,-1,0
       0      .1       0   214.7    .045       0  236.14      .1       0
Bank Sta=214.7,236.14
XS Rating Curve= 0 ,0
Exp/Cntr(USF)=0,0
Exp/Cntr=0.3,0.1

Type RM Length L Ch R = 1 ,742     ,139.9,141.5,142.6
XS GIS Cut Line= 2
1671104.48998712 540160.000629331670716.87155388539999.854733638
#Sta/Elev= 30
       0 1024.87    10.5 1022.97    24.7 1018.29    38.9 1011.62      46 1006.83
    63.8  992.45    81.5  983.11   106.4  967.91   120.5  956.32   134.7  947.58
   152.5  939.07   175.3  934.88  204.74924.0541   212.8  923.29  221.77924.0549
   223.5  924.55   230.5  930.08   251.9  939.47   255.7  941.96   269.6  957.52
   285.8  970.08   303.4  980.07   315.9  988.36     330  994.52   344.2 1006.37
   351.1 1010.84   372.6 1020.65   383.2 1023.42     401 1033.48   419.4 1048.42
#Mann= 3 ,-1,0
       0      .1       0  204.74    .045       0  221.77      .1       0
Bank Sta=204.74,221.77
XS Rating Curve= 0 ,0
Exp/Cntr(USF)=0,0
Exp/Cntr=0.3,0.1

Type RM Length L Ch R = 1 ,600     ,301.8,299.6,297.3
XS GIS Cut Line= 6
1671153.24384743540062.504490092  1671078.262042 540017.40451467
 1671013.9495066539978.8183057611670928.20000617539927.369589761
1670863.88779885539888.7823965851670788.85710901539843.764113918
#Sta/Elev= 30
       0  1018.9    14.6 1014.93    22.3 1011.44    47.6  991.34      62  986.75
    78.7  977.96   102.7  967.66   133.3  950.42   144.8  943.03   160.1  938.48
   171.5   933.4   186.3   929.1   195.9  923.19  202.39920.6027   210.9   919.6
  221.92920.6036   236.5  926.96   253.3  936.04     282  956.77   290.1     964
   297.8  969.64   306.6  974.36   324.6  981.51   343.7  991.85   355.2  999.71
   374.3 1014.61   385.8 1018.34   397.3  1023.8   408.8 1026.93     425 1034.91
#Mann= 3 ,-1,0
       0      .1       0  202.39    .045       0  221.92      .1       0
Bank Sta=202.39,221.92
XS Rating Curve= 0 ,0
Exp/Cntr(USF)=0,0
Exp/Cntr=0.3,0.1

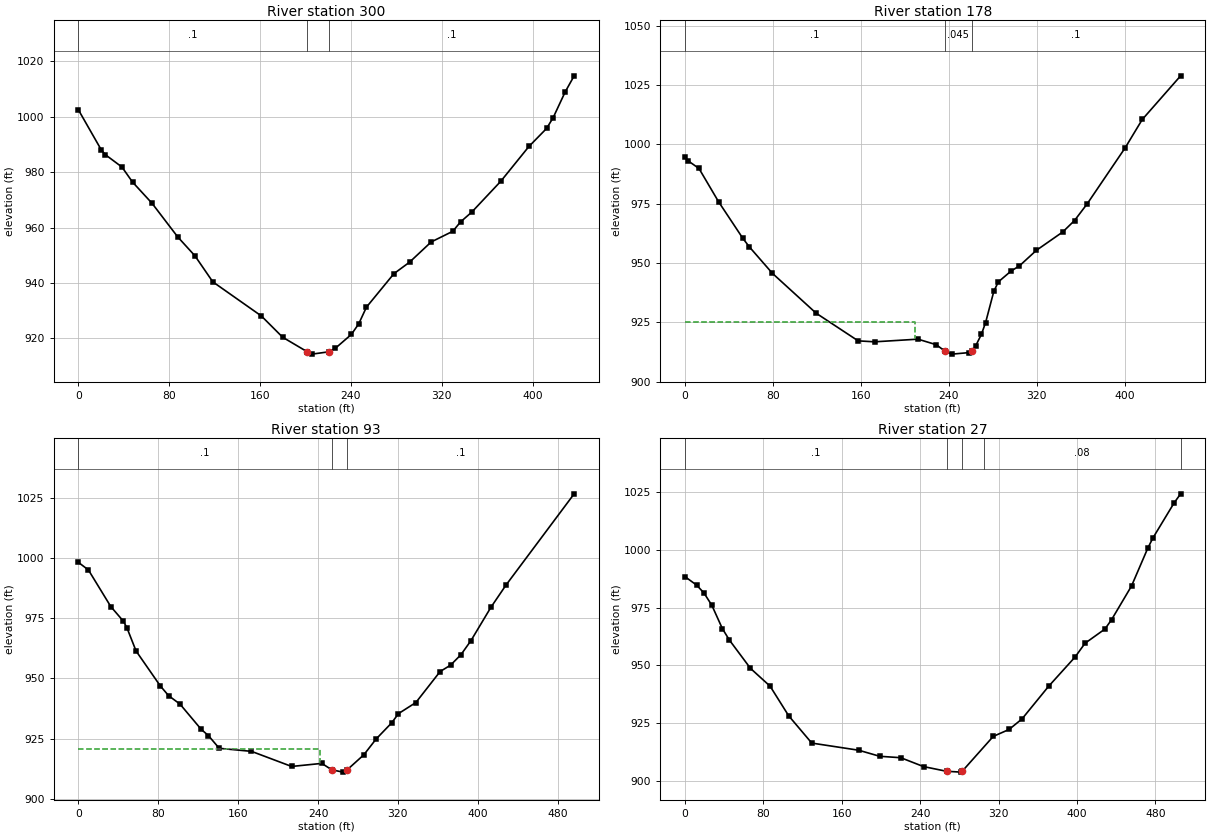
Type RM Length L Ch R = 1 ,300     ,121.3,122.8,128.7
XS GIS Cut Line= 6
1671347.02823676539775.9827534261671263.51134342539749.883068085
1671191.92552859539727.512049839  1671095.616338539698.279496759
 1671019.9672111539673.1424079241670933.30071776539637.378043756
#Sta/Elev= 30
       0 1002.53    20.2  988.04    23.7  986.33    38.4  981.84    47.7  976.43
    64.9  968.76    87.5  956.63   102.7  949.79   118.4  940.41   161.2  928.08
   179.9  920.42  201.63915.1548   205.7  914.32  220.54 915.153   226.3  916.43
   240.4  921.42   246.9  925.25   253.7  931.27   277.9  943.36   291.7  947.52
   310.7   954.8   329.7  958.65   336.6  962.05   346.5   965.6     372  976.71
   396.8  989.28   412.3  995.76   418.1  999.65   428.7 1008.96   436.6 1014.76
#Mann= 3 ,-1,0
       0      .1       0  201.63    .045       0  220.54      .1       0
Bank Sta=201.63,220.54
XS Rating Curve= 0 ,0
Exp/Cntr(USF)=0,0
Exp/Cntr=0.3,0.1

Type RM Length L Ch R = 1 ,178     ,86.8,84.3,86.7
XS GIS Cut Line= 3
1671350.41016981539754.9513502931671196.80084129539615.068812831
1670989.59166196539487.605752995
#Sta/Elev= 30
       0  994.73       3  993.09    12.9  989.86    30.7  975.85    52.9  960.34
    58.7  956.82    79.7  945.65   119.4  928.87   157.7  917.18   172.7  916.78
   212.1   917.9   228.8  915.55  236.26912.9714   243.1  911.59   258.2  912.22
  261.09912.9713   264.6  915.08   269.8  919.95   273.6  924.88   281.1  938.09
   285.2  942.05   296.7  946.59   304.4  948.81   319.8  955.35   343.8   963.1
   354.5  967.92   366.1  975.01   400.5  998.53   416.1 1010.51     451 1028.92
#Mann= 3 ,-1,0
       0      .1       0  236.26    .045       0  261.09      .1       0
#XS Ineff= 2 , 0
          209.03  925.03
Permanent Ineff=
       F       F
Bank Sta=236.26,261.09
XS Rating Curve= 0 ,0
Exp/Cntr(USF)=0,0
Exp/Cntr=0.3,0.1

Type RM Length L Ch R = 1 ,93      ,63.5,66.1,67.6
XS GIS Cut Line= 3
  1671361.522334539747.1074696881671270.66405032539552.971424706
1671003.97210974539460.805827593
#Sta/Elev= 30
       0  998.15    10.1  994.98    32.5  979.81    45.1  973.75    48.8  970.87
    57.8   961.4    82.1  946.91    90.4  942.87   101.8  939.38     123  928.93
   130.3   926.3   141.1  921.05   173.4  919.79   213.6  913.53   243.8   914.8
  253.86 912.128   265.1  911.18  269.18912.1282   285.9  918.37   298.2  924.91
   313.7  931.57   320.6  935.44     338  940.03   362.3  952.89   372.7  955.51
   383.1  959.84   393.1  965.65   413.1  979.48   428.2  988.69   496.5 1026.54
#Mann= 3 ,-1,0
       0      .1       0  253.86    .045       0  269.18      .1       0
#XS Ineff= 2 , 0
          241.52  920.92
Permanent Ineff=
       F       F
Bank Sta=253.86,269.18
XS Rating Curve= 0 ,0
Exp/Cntr(USF)=0,0
Exp/Cntr=0.3,0.1

Type RM Length L Ch R = 1 ,27      ,,,
XS GIS Cut Line= 4
 1671383.6694657539706.9638961211671299.27818174539509.025769662
1671210.50511095539453.9344184281671029.49332954539411.069908952
#Sta/Elev= 30
       0  988.54      12  984.83    19.5  981.44    27.6  976.06    38.3  965.99
    45.4  961.06      67  948.75      87  941.04     106  928.19   129.5   916.4
   177.4   913.3   198.8  910.68   220.3  910.06   243.5  906.22     267  904.18
   282.1  903.82   282.9  904.18   314.6   919.3   330.7  922.29   343.9  926.85
   371.1  941.01   398.1  953.69   408.2  959.63   428.5  965.79   435.2   969.8
   455.6  984.42   472.3  1000.9   477.4  1005.2   499.1 1020.45   505.7 1024.35
#Mann= 5 ,-1,0
       0      .1       0     267    .045       0   282.9      .1       0
  305.18     .08       0  505.67      .1       0
Bank Sta=267,282.9
XS Rating Curve= 0 ,0
Exp/Cntr(USF)=0,0
Exp/Cntr=0.3,0.1
LCMann Table=0

Chan Stop Cuts=-1
Use User Specified Reach Order=0
Composite Channel Slope=5